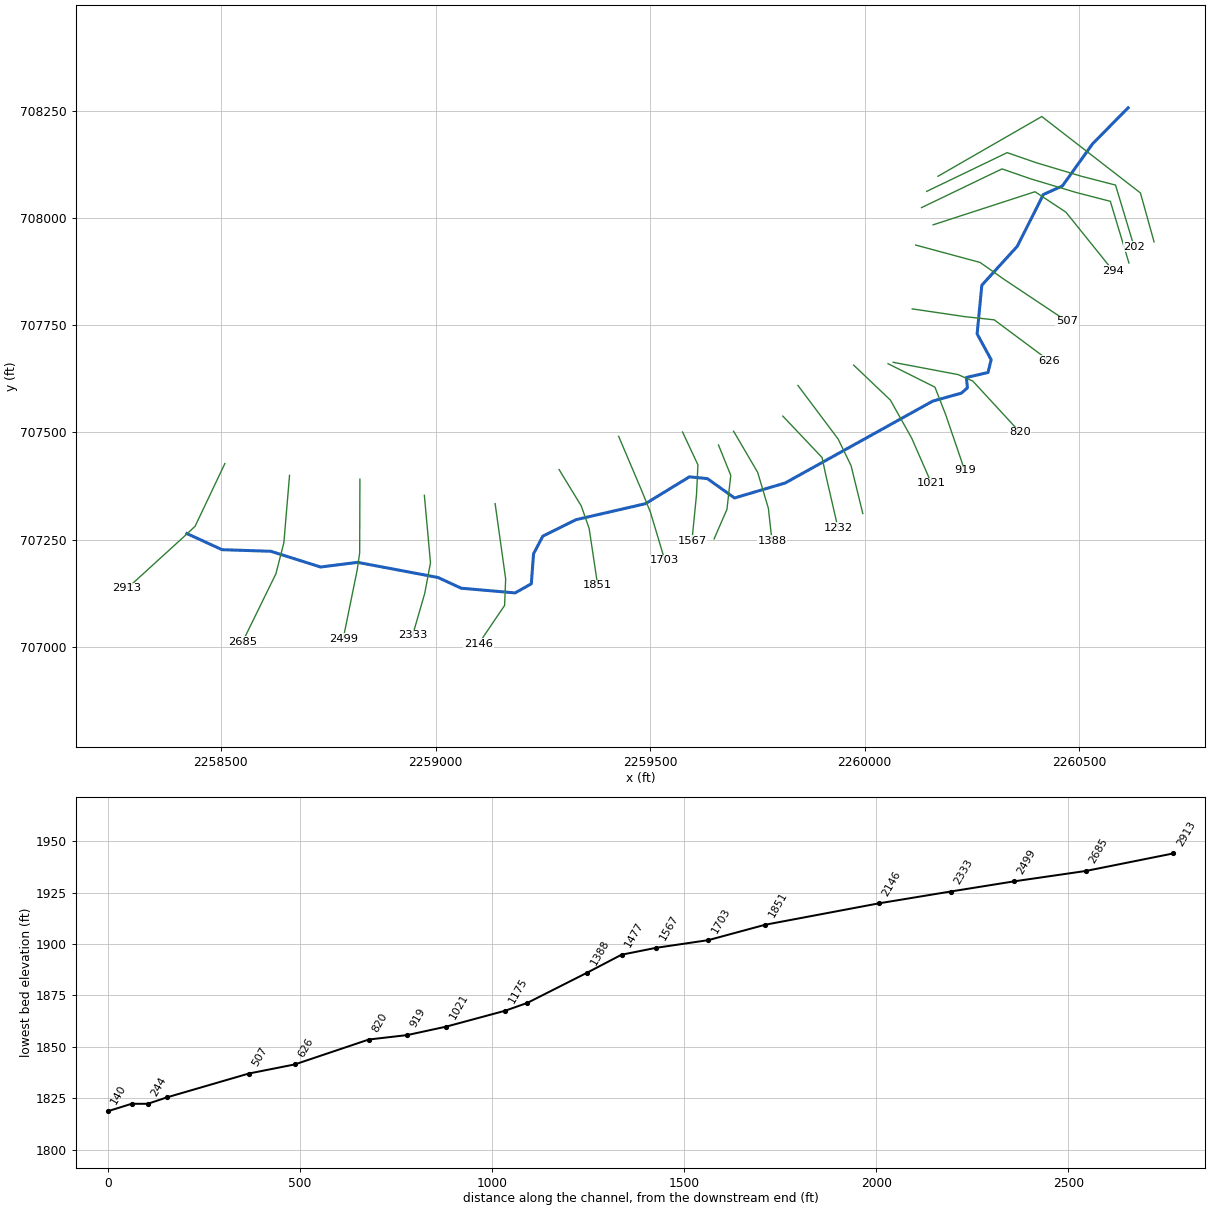
--- TYGVRV1T1.prj (project) ---

Proj Title=TYGVRV1T1
Current Plan=p01
Default Exp/Contr=0,0
English Units
Geom File=g01
Flow File=f01
Plan File=p01
BEGIN DESCRIPTION:
----------MODEL BY WOOD PLC 2022----------
AFH study
Randolph County, WV
HEC-RAS Version: RAS 6.2
Vertical Datum: NAVD88
Projection: NAD 1983 StatePlane West Virginia S FIPS 4702 (US Feet)
Terrain: 1-meter LIDAR (FEMA Region III 3DEP collected 2016-2018)
Land Use: 2019 NLCD
Hydrologic Method:
WV SIR2010-5033 regression equations
Additional Model Notes:
None
END DESCRIPTION:
DSS Export Rating Curves= 0
DSS Export Rating Curve Sorted= 0
DSS Export Volume Flow Curves= 0
DXF OffsetX= 0
DXF OffsetY= 0
DXF ScaleX= 0
DXF ScaleY= 0

--- TYGVRV1T1.p01 (plan) ---

Plan Title=Floodplain
Program Version=6.20
Short Identifier=Floodplain
Geom File=g01
Flow File=f01
Subcritical Flow
K Sum by GR= 0
Std Step Tol= 0.01
Critical Tol= 0.01
Num of Std Step Trials= 20
Max Error Tol= 0.3
Flow Tol Ratio= 0.001
Split Flow NTrial= 30
Split Flow Tol= 0.02
Split Flow Ratio= 0.02
Log Output Level= 0
Friction Slope Method= 1
Unsteady Friction Slope Method= 2
Unsteady Bridges Friction Slope Method= 1
Parabolic Critical Depth
Global Vel Dist= 0 , 0 , 0
Global Log Level= 0
CheckData=True
Encroach Param=-1 ,0,0, 0
Mapping Interval=1HOUR
Computation Time Step Use Courant=        0
Computation Time Step Use Time Series=    0
Computation Time Step Count To Double=0
Computation Time Step Max Doubling=0
Computation Time Step Max Halving=0
Computation Time Step Residence Courant=0
Run HTab= 0
Run UNet= 0
Run Sediment= 0
Run PostProcess= 0
Run WQNet= 0
Run RASMapper=-1
UNET Theta= 0
UNET Theta Warmup= 0
UNET ZTol= 0
UNET ZSATol= 0
UNET MxIter= 0
UNET Max Iter WO Improvement= 0
UNET MaxInSteps= 0
UNET DtIC= 0
UNET DtMin= 0
UNET MaxCRTS= 0
UNET WFStab= 0
UNET SFStab= 0
UNET WFX= 1
UNET SFX= 1
UNET Gravity=32.174
UNET 1D Methodology=Finite Difference
UNET DSS MLevel= 1
UNET Pardiso=0
UNET DZMax Abort= 0
UNET Use Existing IB Tables= 0
UNET Froude Reduction=False
UNET Froude Limit= 0
UNET Froude Power= 0
UNET D1 Cores= 0
UNET WindReference=Eulerian
UNET WindDragFormulation=Hsu (1988)
UNET D2 Coriolis=0
UNET D2 Cores= 0
UNET D2 Theta= 1
UNET D2 Theta Warmup= 1
UNET D2 Z Tol= 0.01
UNET D2 Volume Tol= 0.01
UNET D2 Max Iterations= 20
UNET D2 Equation= 0
UNET D2 RampUpFraction=0.1
UNET D2 TimeSlices= 1
UNET D2 Turbulence Formulation=Non-Conservative (original)
UNET D2 Eddy Viscosity=0.3
UNET D2 Transverse Eddy Viscosity=0.1
UNET D2 Smagorinsky Mixing=0
UNET D2 BCVolumeCheck=0
UNET D2 Cores=0
UNET D2 SolverType=PARDISO (Direct)
UNET D2 Minimum Iterations= 2147483647
UNET D2 Maximum Iterations= 2147483647
UNET D2 Restart Number= 10
UNET D2 Relaxation Coeff=1.3
UNET D2 SOR Precondition Iterations= 10
UNET D2 ILUT Maximum Fill= 8
UNET D2 ILUT Tolerance=1E-08
UNET D1D2 MaxIter= 0
UNET D1D2 ZTol=0.01
UNET D1D2 QTol=0.1
UNET D1D2 MinQTol=1
Write IC File= 0
Write IC File at Fixed DateTime=0
Write IC File at Sim End=0
Echo Input=False
Echo Parameters=False
Echo Output=False
Write Detailed= 0
HDF Write Warmup=0
HDF Write Time Slices=0
HDF Flush=0
HDF Compression= 1
HDF Chunk Size= 1
HDF Spatial Parts= 1
HDF Use Max Rows=0
HDF Fixed Rows= 1
Calibration Method= 0
Calibration Iterations= 20
Calibration Max Change=0.05
Calibration Tolerance=0.2
Calibration Maximum=1.5
Calibration Minimum=0.5
Calibration Optimization Method= 1
WQ AD Non Conservative
WQ ULTIMATE=-1
WQ Max Comp Step=1HOUR
WQ Output Interval=15MIN
WQ Output Selected Increments= 0
WQ Output face flow=0
WQ Output face velocity=0
WQ Output face area=0
WQ Output face dispersion=0
WQ Output cell volume=0
WQ Output cell surface area=0
WQ Output cell continuity=0
WQ Output cumulative cell continuity=0
WQ Output face conc=0
WQ Output face dconc_dx=0
WQ Output face courant=0
WQ Output face peclet=0
WQ Output face adv mass=0
WQ Output face disp mass=0
WQ Output cell mass=0
WQ Output cell source sink temp=0
WQ Output nsm pathways=0
WQ Output nsm derived pathways=0
WQ Create Restart=0
WQ Fixed Restart=0
WQ System Summary=0
WQ Write To DSS=0
Sorting and Armoring Iterations= 10
XS Update Threshold= 0.02
Bed Roughness Predictor= 0
Hydraulics Update Threshold= 0.02
Energy Slope Method= 1
Volume Change Method= 1
Sediment Retention Method= 0
Sediment TS Multiplier= 1
Warm Up Method= 0
XS Weighting Method= 0
Number of US Weighted Cross Sections= 1
Number of DS Weighted Cross Sections= 1
Upstream XS Weight=0
Main XS Weight=1
Downstream XS Weight=0
Number of DS XS's Weighted with US Boundary= 1
Upstream Boundary Weight= 1
Weight of XSs Associated with US Boundary= 0
Number of US XS's Weighted with DS Boundary= 1
Downstream Boundary Weight= 0.5
Weight of XSs Associated with DS Boundary= 0.5
Percentile Method= 0
Sediment Output Level= 3
Mass or Volume Output= 0
Output Increment Type= 1
Profile and TS Output Increment= 1
Transport Output Increment 1
XS Output Flag= 0
XS Output Increment= 10
Read HDF5 Sediment Hotstart= 0
Sediment Hotstart Type= 0
Write Gradation File= 0
Read Gradation Hotstart= 0
Write HDF5 File= 1
Write Binary Output= 1
Write DSS Sediment File= 0
DSS Sediment Output Type= 1
SV Curve= 0
Specific Gage Flag= 0
Subcell Erosion Methods= 0
Subcell Deposition Methods= 0
Advection Scheme= 1
Matrix Solver= 0
Implicit Weighting Factor= 1
Maximum Outer Loop Convergence Iterations= 5
Convergence Maximum Absolute= 0.001
Convergence RMSE= 0.0001
Grain Fractions Max Abs Error= 0.001
Max Subgrid Regions= 1
Max Subgrid Length Scale= 3.402823E+38
Initial Layer Thickness= 3.402823E+38
Min Layer Thickness= 3.402823E+38
Max Layer Thickness= 3.402823E+38
Number of Layers= 5

--- TYGVRV1T1.f01 (steady flow) ---

Flow Title=Flow
Program Version=6.20
Number of Profiles= 1
Profile Names=P100yr
River Rch & RM=TYGVRV1T1,Main,2913
     438
Boundary for River Rch & Prof#=TYGVRV1T1,Main            , 1
Up Type= 0
Dn Type= 3
Dn Slope=0.0581
DSS Import GetInterval= 0
DSS Import GetPeak= 0
DSS Import FillOption= 0

--- TYGVRV1T1.g01 (geometry) ---

Geom Title=Geometry
Program Version=6.20

River Reach=TYGVRV1T1       ,Main
Reach XY= 30
2258420.71315183707264.425535902     2258502.704707226.832000017
2258616.25300001707223.1260000172258732.30500005707186.466999993
2258818.24200001707197.3180000042259005.65000001707162.107999995
2259059.90100002707137.0660000152259185.43000002707126.136999995
      2259223.19707147.4050000012259228.39800003707217.283000022
2259250.10000002707258.5160000182259327.35700001707296.709999993
2259489.24900003      707334.0372259591.46300001      707396.537
     2259633.346707392.4130000032259696.52950882707347.319108105
2259814.58700003707382.1930000192260158.33991182707572.909138316
2260225.18082365707591.5567896052260239.21955828 707603.84597405
2260236.73990954707627.9471894182260287.11630265707639.605961953
2260294.43600005707669.4839999972260261.79700001707729.554000005
2260272.77800001707843.0520000012260355.46000002707933.763999999
2260416.00700004      708054.2062260460.47000001708074.307000011
2260530.67700002708172.2190000122260613.58252741708256.399599881

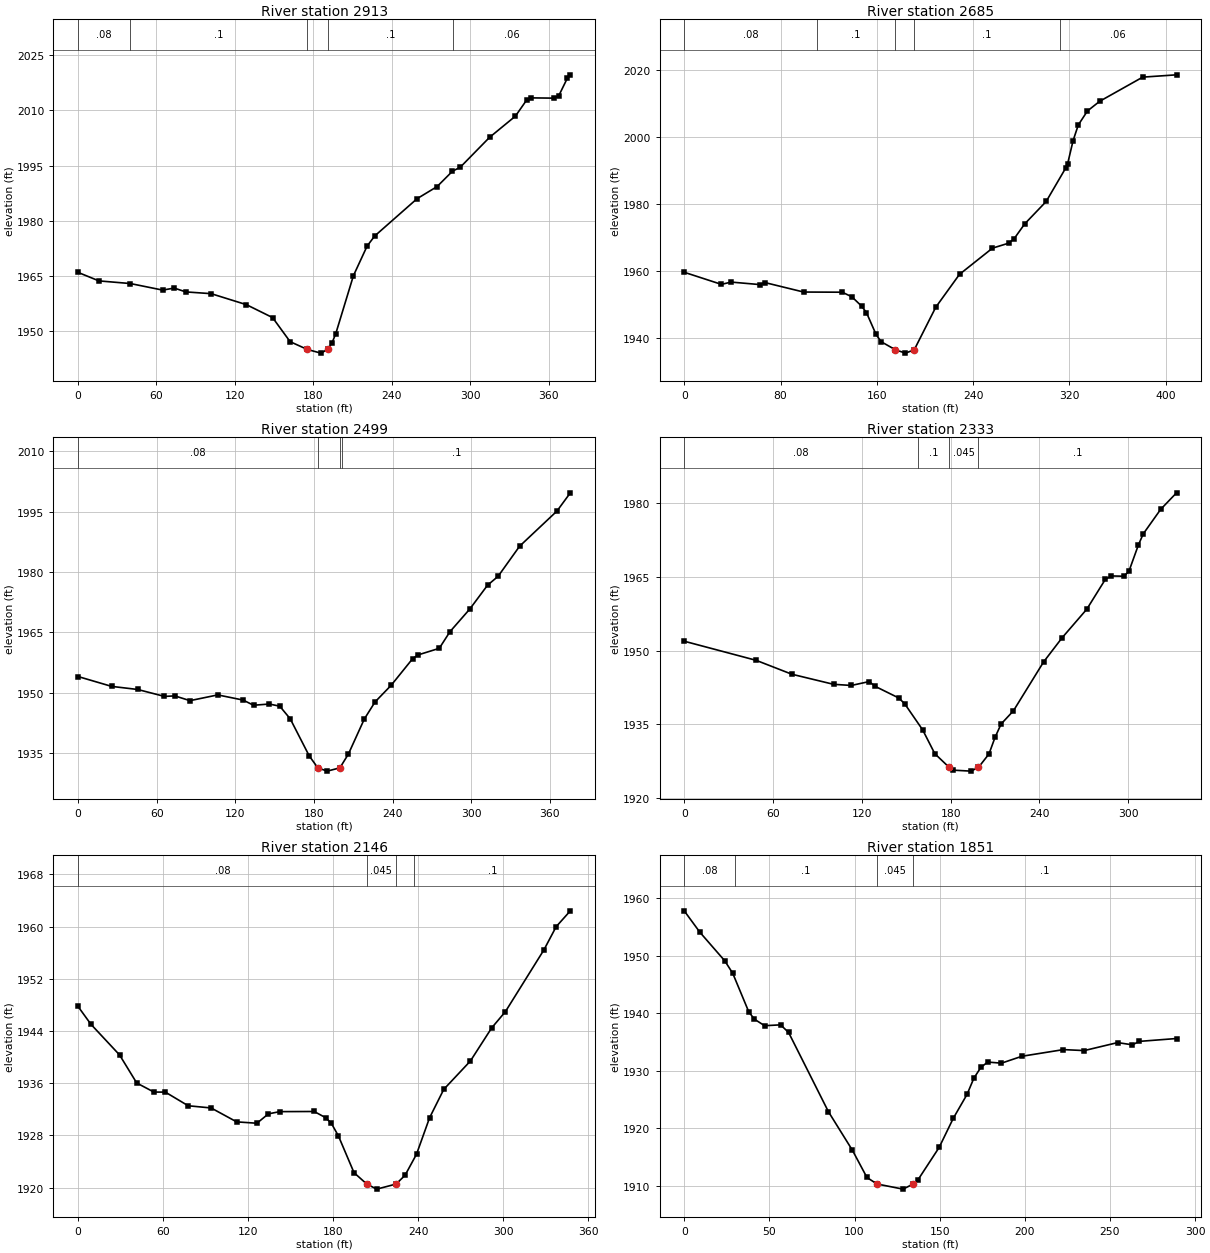
Type RM Length L Ch R = 1 ,2913    ,221.4,228.4,230
XS GIS Cut Line= 4
2258509.33448843 707427.625261272258439.91893429707281.414585931
 2258414.1620833707257.3934836122258281.57582084707136.567298901
#Sta/Elev= 30
       0 1965.99      16 1963.68      40 1962.96    64.7 1961.18    73.6 1961.73
    82.4 1960.69   101.8 1960.21   128.8 1957.22   148.8 1953.71   162.2 1947.17
  175.341945.061   185.7 1944.06  190.871945.061   194.3  1946.9   197.1 1949.34
   210.6 1965.09   221.1 1973.15   226.9 1975.88   259.3 1986.01   274.6  1989.3
   286.3 1993.45   292.4 1994.58   314.7 2002.66   334.5 2008.43     343 2012.76
   346.1 2013.39   363.7 2013.32   367.5 2013.86   374.2 2018.73   376.5 2019.65
#Mann= 5 ,-1,0
       0     .08       0      40      .1       0  175.34    .045       0
  190.87      .1       0  287.07     .06       0
Bank Sta=175.34,190.87
XS Rating Curve= 0 ,0
Exp/Cntr(USF)=0,0
Exp/Cntr=0.3,0.1

Type RM Length L Ch R = 1 ,2685    ,185.2,186.3,186.9
XS GIS Cut Line= 4
2258659.92198814707399.9985791562258646.72799762707243.234037124
2258628.17895789707170.6551856122258550.40853378 707011.94003437
#Sta/Elev= 30
       0 1959.64    30.9 1956.03      39 1956.71      63 1955.96    67.1 1956.56
    99.2 1953.74   131.3 1953.69   139.3 1952.31   147.3 1949.56   151.4  1947.6
   159.4 1941.07   163.6 1938.92   175.51936.502   183.8 1935.51   191.11936.501
     209 1949.22   228.7 1959.02   256.1 1966.84   269.5 1968.32     274 1969.61
   282.9 1974.09   300.7 1980.76     317 1990.79   318.5 1991.99   323.1 1998.96
   327.4 2003.61     335 2007.78   345.2 2010.67   380.9 2017.87     409 2018.56
#Mann= 5 ,-1,0
       0     .08       0     110      .1       0   175.5    .045       0
   191.1      .1       0  312.23     .06       0
Bank Sta=175.5,191.1
XS Rating Curve= 0 ,0
Exp/Cntr(USF)=0,0
Exp/Cntr=0.3,0.1

Type RM Length L Ch R = 1 ,2499    ,165.9,165.4,165.3
XS GIS Cut Line= 4
 2258823.8904587707391.1052918522258823.31711916707219.406917426
2258817.58980357707179.8363733482258784.88483832707019.169284823
#Sta/Elev= 30
       0 1953.99    25.6 1951.54    45.5 1950.77    65.9 1949.05    73.9 1949.17
    85.4 1947.99   106.6 1949.42   125.9 1948.14   133.9 1946.85   145.9 1947.15
   153.9 1946.62   161.9 1943.47   176.4 1934.25  182.951931.284   190.1 1930.47
  199.791931.286   206.3 1934.73   218.4 1943.41   226.6 1947.67   238.9 1951.81
   255.2 1958.39   259.3 1959.35   275.6    1961   283.8 1965.15     299 1970.81
   312.4 1976.68   320.5 1978.91   336.9 1986.39   365.4 1995.13   375.6 1999.66
#Mann= 4 ,-1,0
       0     .08       0  182.95    .045       0  199.79     .08       0
   201.7      .1       0
Bank Sta=182.95,199.79
XS Rating Curve= 0 ,0
Exp/Cntr(USF)=0,0
Exp/Cntr=0.3,0.1

Type RM Length L Ch R = 1 ,2333    ,185.8,186.9,188.6
XS GIS Cut Line= 4
2258974.00163743 707353.61848496 2258988.2709231707196.342086565
2258974.79521318707124.653627051 2258946.4801254707026.927621492
#Sta/Elev= 30
       0 1951.89    48.6 1948.01    72.7 1945.19   100.9 1943.14   112.9 1942.91
     125  1943.7     129 1942.73     145 1940.36     149 1939.17   161.1 1933.89
   169.3 1929.06     1791926.284   181.5 1925.72   193.7 1925.52  198.811926.284
   205.9 1929.01     210 1932.38   214.1 1935.09   222.4 1937.76   242.8 1947.69
   255.3 1952.59     272  1958.4   284.5 1964.44   288.6 1965.14     297 1965.08
   300.4 1966.05   306.8  1971.4   310.1 1973.67   321.9 1978.66   332.6 1982.01
#Mann= 4 ,-1,0
       0     .08       0  157.92      .1       0     179    .045       0
  198.81      .1       0
Bank Sta=179,198.81
XS Rating Curve= 0 ,0
Exp/Cntr(USF)=0,0
Exp/Cntr=0.3,0.1

Type RM Length L Ch R = 1 ,2146    ,295.2,295.3,302.5
XS GIS Cut Line= 4
2259138.87839671707334.1803642152259163.40689368707158.673852894
2259160.96356575707097.0073168822259100.26012866707007.218196829
#Sta/Elev= 30
       0 1947.76     9.1 1945.03    29.3 1940.33    41.4 1936.03    53.5 1934.64
    61.6 1934.63    77.7 1932.54    93.9  1932.2   111.9 1930.07   126.2 1929.86
   134.3  1931.3   142.4 1931.64   166.6 1931.66   174.7 1930.71   178.7 1929.85
   183.7 1927.91   194.7 1922.28   203.71920.537   210.7 1919.76  224.371920.538
   230.7 1921.88   238.8 1925.12     248  1930.7     258 1935.05   276.8  1939.4
   291.8 1944.47   301.5 1946.97   328.7 1956.45   337.3 1959.99   347.3 1962.42
#Mann= 4 ,-1,0
       0     .08       0   203.7    .045       0  224.37     .08       0
  237.21      .1       0
Bank Sta=203.7,224.37
XS Rating Curve= 0 ,0
Exp/Cntr(USF)=0,0
Exp/Cntr=0.3,0.1

Type RM Length L Ch R = 1 ,1851    ,148.9,148.2,148.5
XS GIS Cut Line= 4
2259287.86747726707413.5199924322259339.60279701 707328.61038447
2259357.94847317707276.2162755112259377.83251548707143.571972696
#Sta/Elev= 30
       0 1957.82     9.2 1954.09    23.8 1949.12    28.5 1946.94    37.9 1940.24
    41.2 1938.96    47.2 1937.82    56.6 1937.97    61.3 1936.64    84.7 1922.84
    98.8 1916.12   107.3  1911.4  113.191910.264   128.5 1909.37   134.51910.264
   137.1 1910.91   149.7 1916.63     158  1921.7   166.1 1925.87   170.1 1928.69
   174.2 1930.56   178.2 1931.49   186.3  1931.3   198.3  1932.5   222.7 1933.66
   234.9 1933.49   254.5 1934.88   263.2 1934.49   267.2 1935.09   289.1 1935.59
#Mann= 4 ,-1,0
       0     .08       0      30      .1       0  113.19    .045       0
   134.5      .1       0
Bank Sta=113.19,134.5
XS Rating Curve= 0 ,0
Exp/Cntr(USF)=0,0
Exp/Cntr=0.3,0.1

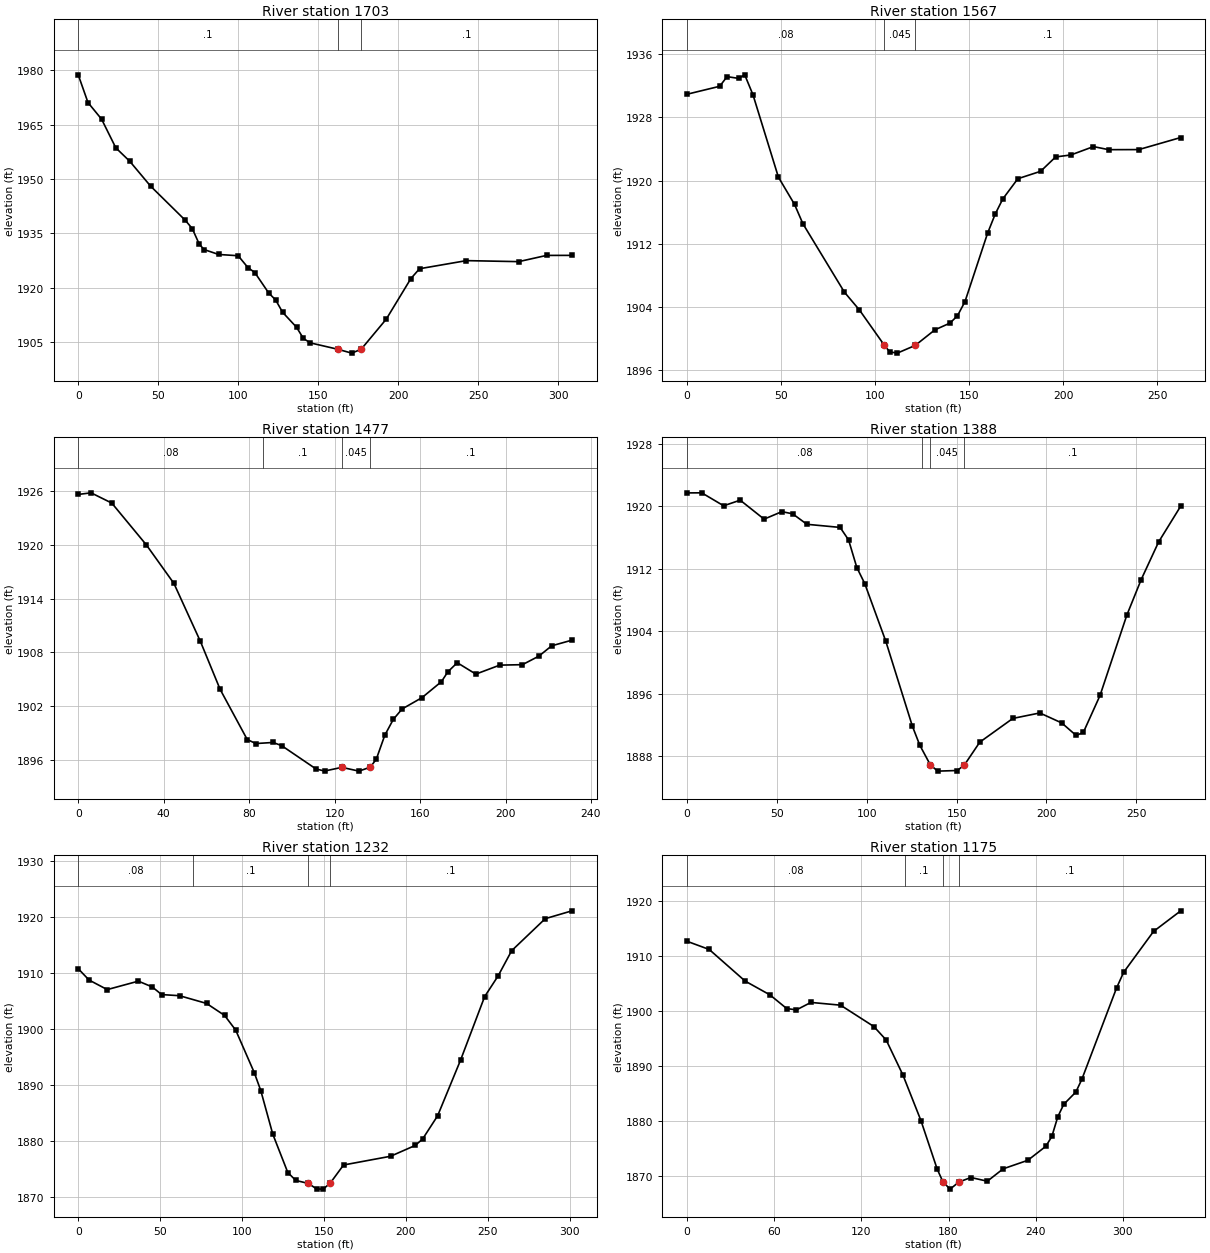
Type RM Length L Ch R = 1 ,1703    ,138.6,136,131.1
XS GIS Cut Line= 4
2259426.69921361707490.8142815192259480.09439714707364.953189704
2259500.75959312707313.922807796 2259534.3142718707201.941997447
#Sta/Elev= 30
       0 1978.72     6.1 1971.06    14.6 1966.48    23.5 1958.56    32.2 1954.86
    45.2 1948.01      67 1938.53    71.3 1936.26    75.6 1932.04    78.6 1930.49
    87.8 1929.12     100 1928.77   106.1  1925.5   110.4 1924.13   119.1 1918.48
   123.4 1916.58   127.8 1913.15   136.5 1909.02   140.8 1905.92   145.1 1904.71
  162.211902.958     171 1901.88  176.911902.956   192.6 1911.27     208 1922.48
   213.4 1925.18   242.7 1927.42   275.4 1927.14   292.8 1928.86   308.7 1928.87
#Mann= 3 ,-1,0
       0      .1       0  162.21    .045       0  176.91      .1       0
Bank Sta=162.21,176.91
XS Rating Curve= 0 ,0
Exp/Cntr(USF)=0,0
Exp/Cntr=0.3,0.1

Type RM Length L Ch R = 1 ,1567    ,91.6,89.7,88.2
XS GIS Cut Line= 4
 2259575.5642414707500.951461839  2259611.354508707424.450758942
2259608.03407492 707354.965860182259597.35583166707246.967541066
#Sta/Elev= 30
       0 1930.93    17.4 1931.94    21.3 1933.16    27.4 1932.94    30.7 1933.39
    35.1 1930.85    48.6 1920.43    57.2 1916.97    61.6 1914.54    83.7 1905.86
    91.7  1903.6  104.971899.121   107.8  1898.3   111.8 1898.14  121.381899.121
   131.8 1901.09   139.8 1901.94   143.8 1902.87   147.8 1904.67   159.8 1913.32
   163.9 1915.77   167.9 1917.67   175.9 1920.23     188 1921.17     196 1922.99
   204.1 1923.24   216.1  1924.3   224.2 1923.91   240.2 1923.92   262.5 1925.45
#Mann= 3 ,-1,0
       0     .08       0  104.97    .045       0  121.38      .1       0
Bank Sta=104.97,121.38
XS Rating Curve= 0 ,0
Exp/Cntr(USF)=0,0
Exp/Cntr=0.3,0.1

Type RM Length L Ch R = 1 ,1477    ,87.2,89,91.5
XS GIS Cut Line= 4
2259659.28787135 707470.72190237 2259687.8723828707399.963521576
2259678.96901038707320.7703669132259648.97870329707251.886380313
#Sta/Elev= 30
       0 1925.59       6 1925.77    15.7 1924.63    31.9 1919.97    44.8 1915.68
    57.2 1909.22    66.4  1903.9    79.1 1898.31    83.1 1897.86    91.2 1897.98
    95.2 1897.63   111.3 1895.03   115.3  1894.8   123.4 1895.21   131.4 1894.79
  136.67 1895.23   139.5 1896.11   143.5 1898.79   147.5 1900.56   151.6 1901.71
   160.9 1902.97     170 1904.75     173 1905.84   177.4 1906.86   186.1 1905.59
   197.3 1906.59   207.9 1906.64   215.6 1907.59   221.6 1908.74   231.1 1909.37
#Mann= 4 ,-1,0
       0     .08       0   86.31      .1       0   123.4    .045       0
  136.67      .1       0
Bank Sta=123.4,136.67
XS Rating Curve= 0 ,0
Exp/Cntr(USF)=0,0
Exp/Cntr=0.3,0.1

Type RM Length L Ch R = 1 ,1388    ,155.6,155.9,155.2
XS GIS Cut Line= 4
2259694.48338284707502.7512235322259750.53146403707406.996516138
2259775.46372717707323.3313156592259783.91785464707247.338232148
#Sta/Elev= 30
       0 1921.74     8.2 1921.75    20.4 1920.09    29.6 1920.81    42.9 1918.38
    52.8 1919.34    58.8 1919.06    66.7 1917.72    85.2 1917.32    89.9 1915.72
    94.5 1912.18    98.9 1910.13   110.6 1902.75   125.4 1891.87   129.5 1889.44
  135.42  1886.9   139.5 1886.11   150.4 1886.19  154.351886.901   162.9 1889.82
   181.3 1892.86   196.3 1893.56   208.5 1892.28   216.5 1890.68   220.5 1891.06
   229.8  1895.8   244.7 1906.08   252.7 1910.64   262.4 1915.46   274.7 1920.05
#Mann= 4 ,-1,0
       0     .08       0  130.95      .1       0  135.42    .045       0
  154.35      .1       0
Bank Sta=135.42,154.35
XS Rating Curve= 0 ,0
Exp/Cntr(USF)=0,0
Exp/Cntr=0.3,0.1

Type RM Length L Ch R = 1 ,1232    ,55.3,57.6,59
XS GIS Cut Line= 4
2259809.15803345707537.9999091032259900.53628728707441.586615992
2259909.05020569707401.4070588822259937.71730595707277.310273188
#Sta/Elev= 30
       0 1910.75     6.6 1908.73    17.7 1907.02    36.7 1908.53    45.2 1907.49
    50.9 1906.13    61.8 1905.93    78.3 1904.55    89.3 1902.41    96.1 1899.78
   107.4 1892.21   111.4 1888.98   118.7 1881.22   127.9 1874.34   132.8 1872.93
  140.42  1872.4   145.5 1871.41   149.4 1871.38   153.7 1872.42   161.9 1875.69
   190.6 1877.25   205.6 1879.18   210.1 1880.31   219.3 1884.47   233.4 1894.49
     248 1905.76   256.2 1909.45   264.5 1913.97     285 1919.69   301.3 1921.09
#Mann= 4 ,-1,0
       0     .08       0      70      .1       0  140.42    .045       0
   153.7      .1       0
Bank Sta=140.42,153.7
XS Rating Curve= 0 ,0
Exp/Cntr(USF)=0,0
Exp/Cntr=0.3,0.1

Type RM Length L Ch R = 1 ,1175    ,153,153.5,153.7
XS GIS Cut Line= 4
2259844.39071565707609.3958433672259937.99629463707484.618933005
 2259968.0791644707422.7176432932259995.46478881707311.045261483
#Sta/Elev= 30
       0  1912.6    15.3 1911.11      40 1905.37    57.1 1902.86    68.6 1900.38
    75.3 1900.13    85.3 1901.49   105.7 1900.99   128.6 1897.11   137.1 1894.66
   148.6 1888.31     161 1880.03   172.2  1871.2   176.2 1868.87   181.1 1867.57
   187.1 1868.86   195.4 1869.68   206.7 1869.01   217.6 1871.26   234.6 1872.81
     247 1875.36   251.1 1877.14   255.2 1880.72   259.3 1882.98   267.6  1885.2
   271.7 1887.49   295.6 1904.09   300.5 1906.96   321.1 1914.39   339.8 1918.13
#Mann= 4 ,-1,0
       0     .08       0     150      .1       0   176.2    .045       0
   187.1      .1       0
Bank Sta=176.2,187.1
XS Rating Curve= 0 ,0
Exp/Cntr(USF)=0,0
Exp/Cntr=0.3,0.1

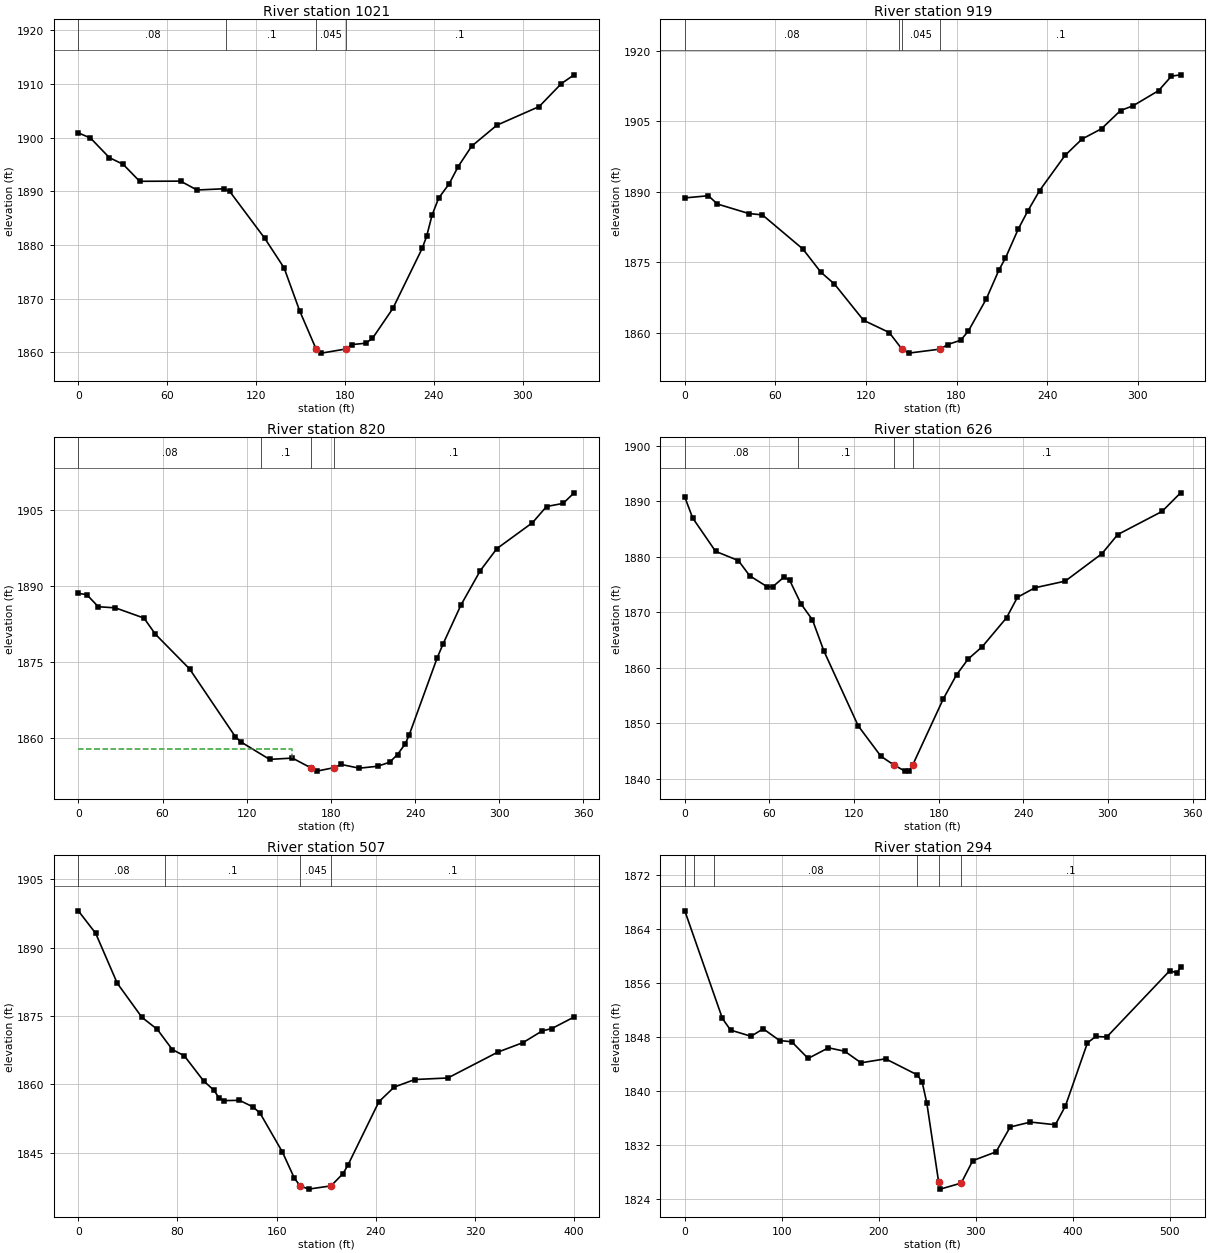
Type RM Length L Ch R = 1 ,1021    ,102.7,101.8,99.3
XS GIS Cut Line= 4
2259974.20370836707656.798032273 2260059.6622647707575.408930994
2260109.18772495707487.0204950812260155.47697582707381.338476084
#Sta/Elev= 30
       0 1900.87     8.2 1899.91    20.9 1896.27    30.3    1895    41.4 1891.85
      69 1891.88    80.1 1890.23      98 1890.45   102.2 1889.96   125.9  1881.2
   138.9 1875.71   149.4 1867.71  160.511860.589   164.1 1859.83  180.411860.591
   184.8 1861.43   193.9 1861.67   198.5 1862.56   212.3 1868.15   232.1 1879.34
   235.1 1881.59   238.8 1885.56   243.2  1888.7   250.3 1891.37   256.4 1894.59
   265.5 1898.39   282.5  1902.3   311.1 1905.78   326.1 1910.07   334.7 1911.69
#Mann= 4 ,-1,0
       0     .08       0     100      .1       0  160.51    .045       0
  180.41      .1       0
Bank Sta=160.51,180.41
XS Rating Curve= 0 ,0
Exp/Cntr(USF)=0,0
Exp/Cntr=0.3,0.1

Type RM Length L Ch R = 1 ,919     ,90.5,99.7,103.7
XS GIS Cut Line= 4
2260054.23379783707660.1609528962260163.50917946707605.523262079
 2260188.5782376707541.2436258232260232.93118662707411.398760587
#Sta/Elev= 30
       0  1888.7    15.6 1889.16    21.6  1887.4    42.4 1885.38    51.4 1885.09
    78.2 1877.84    90.1 1872.92    99.1  1870.4   118.4 1862.69   135.4 1860.09
     144 1856.49   148.3 1855.71   169.3 1856.57   174.1 1857.54   182.7 1858.44
   187.8  1860.4   199.7 1867.23   208.1 1873.41   212.4 1875.92   220.8 1882.04
     227 1885.82     235 1890.26   251.8 1897.72   263.1 1901.21     276  1903.4
   288.6 1907.27   296.9 1908.28   313.8  1911.5   322.3 1914.57   328.4 1914.86
#Mann= 4 ,-1,0
       0     .08       0  142.17      .1       0     144    .045       0
   169.3      .1       0
Bank Sta=144,169.3
XS Rating Curve= 0 ,0
Exp/Cntr(USF)=0,0
Exp/Cntr=0.3,0.1

Type RM Length L Ch R = 1 ,820     ,189.8,193,192.9
XS GIS Cut Line= 4
2260066.21795502707663.3561687382260217.38082485707634.770390923
2260251.68746946707619.7009141852260361.52488268707500.468068178
#Sta/Elev= 30
       0 1888.64     6.1 1888.36    14.2 1885.99    26.4 1885.77    46.8 1883.75
    54.9 1880.58    79.3 1873.72   111.9 1860.35     116  1859.3   136.3 1855.88
   152.6 1856.13   165.6 1854.23     170 1853.56  181.99 1854.23   187.5 1854.87
   200.2 1854.14   213.3 1854.52   221.9 1855.32   227.5 1856.84   233.1 1858.98
   235.9 1860.76   255.7 1875.85     260 1878.67   272.7 1886.32   286.5 1893.11
   298.3 1897.45   323.7 1902.57   333.7 1905.76   345.5 1906.37   353.4 1908.46
#Mann= 4 ,-1,0
       0     .08       0     130      .1       0   165.6    .045       0
  181.99      .1       0
#XS Ineff= 2 , 0
          151.99 1857.89
Permanent Ineff=
       F       F
Bank Sta=165.6,181.99
XS Rating Curve= 0 ,0
Exp/Cntr(USF)=0,0
Exp/Cntr=0.3,0.1

Type RM Length L Ch R = 1 ,626     ,124.4,119.2,113.9
XS GIS Cut Line= 4
2260110.61306419707787.8353987122260235.67267569707769.416574356
2260301.55161313707762.3486666892260428.95032501 707667.55565581
#Sta/Elev= 30
       0 1890.72     5.6 1886.96    21.8 1880.97      38  1879.3      46 1876.57
    58.2 1874.63    62.2 1874.57    70.3 1876.33    74.4 1875.73    82.4  1871.5
    90.5 1868.64    98.6 1863.04   122.9 1849.59     139 1844.11  148.341842.521
   156.1 1841.43   159.1 1841.53  161.53 1842.52   183.2  1854.4   192.7 1858.78
   200.9  1861.6   210.9 1863.82   228.1 1869.02   235.8  1872.7   248.2 1874.41
   269.7 1875.61   295.7 1880.54   306.9 1883.98   338.3 1888.14   351.5 1891.49
#Mann= 4 ,-1,0
       0     .08       0      80      .1       0  148.34    .045       0
  161.53      .1       0
Bank Sta=148.34,161.53
XS Rating Curve= 0 ,0
Exp/Cntr(USF)=0,0
Exp/Cntr=0.3,0.1

Type RM Length L Ch R = 1 ,507     ,212.5,213.5,213
XS GIS Cut Line= 4
 2260118.6513372707936.5363654712260268.63715512707896.064001904
2260324.11682108707856.9608734242260471.19895404707758.863482988
#Sta/Elev= 30
       0 1898.06      14 1893.12    31.4 1882.18    51.3  1874.7    63.7 1872.06
    75.8 1867.64    85.5 1866.26     101 1860.77   109.3 1858.73   113.4 1857.08
   117.6 1856.43     130  1856.5     141 1855.04   146.6 1853.68   164.6 1845.18
   174.3 1839.41  178.951837.735   185.8 1837.02  203.861837.735   213.5 1840.41
   217.4 1842.24   242.5  1856.2   254.8  1859.4   271.4 1861.06   298.1  1861.4
   338.5 1867.08   358.7 1869.15   374.2 1871.72     382 1872.24     400 1874.78
#Mann= 4 ,-1,0
       0     .08       0      70      .1       0  178.95    .045       0
  203.86      .1       0
Bank Sta=178.95,203.86
XS Rating Curve= 0 ,0
Exp/Cntr(USF)=0,0
Exp/Cntr=0.3,0.1

Type RM Length L Ch R = 1 ,294     ,47.4,49.4,50.7
XS GIS Cut Line= 4
2260159.23768819707983.6554306652260396.59921058708060.782040945
2260468.71652716708013.1255685832260578.62455118707876.499726901
#Sta/Elev= 30
       0 1866.74    38.8 1850.75    47.2 1849.03    68.3 1848.11    80.9 1849.22
    97.7 1847.48   110.3 1847.29   127.2 1844.82   148.2  1846.4     165 1845.88
   181.8 1844.17   207.1 1844.76     240 1842.36   244.9 1841.26   249.6 1838.21
  261.811826.475   263.5 1825.41   285.1 1826.31     297 1829.64     321 1830.94
   335.6 1834.63   356.5 1835.37   382.2 1834.97   392.6 1837.77   415.3 1847.13
   423.8 1848.08   435.2    1848   500.2 1857.85   507.5 1857.53   511.4 1858.36
#Mann= 6 ,-1,0
       0     .08       0      10      .1       0      30     .08       0
     240      .1       0  261.81    .045       0   285.1      .1       0
Bank Sta=261.81,285.1
XS Rating Curve= 0 ,0
Exp/Cntr(USF)=0,0
Exp/Cntr=0.3,0.1

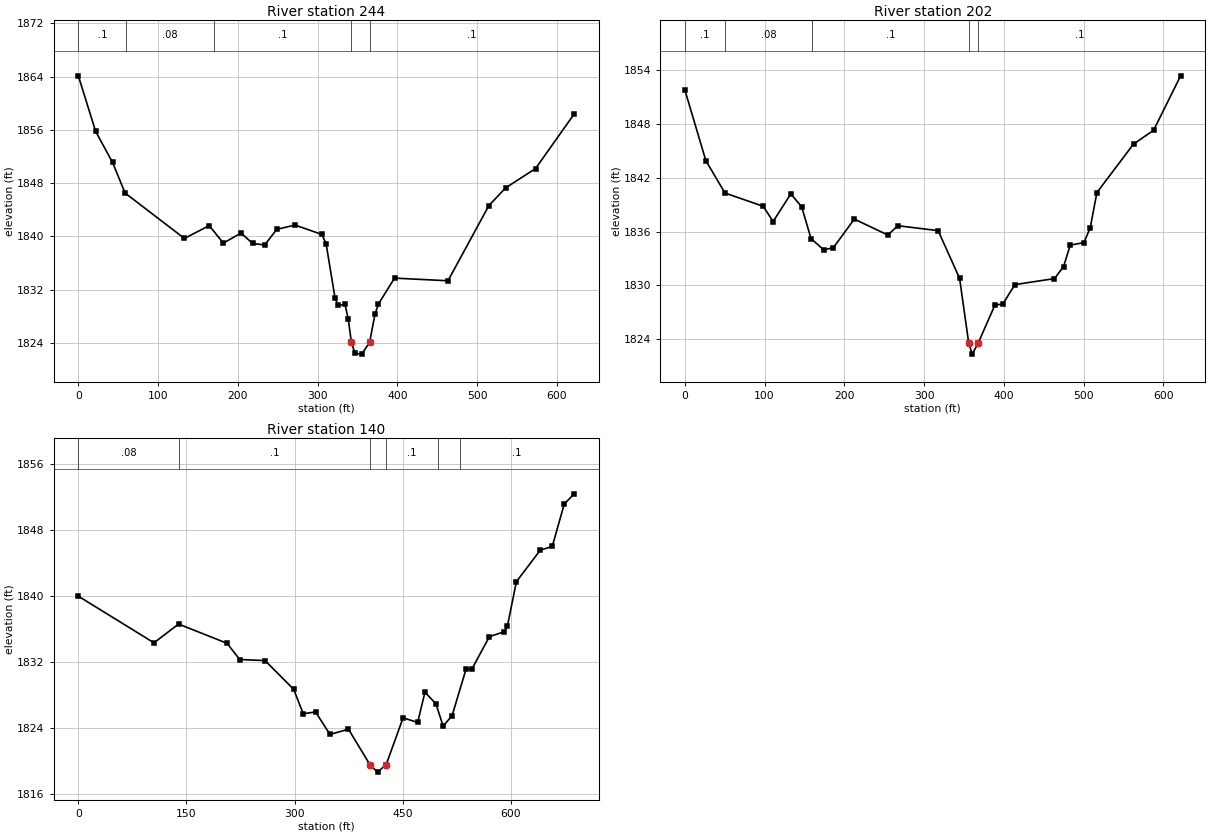
Type RM Length L Ch R = 1 ,244     ,42.4,42.2,40.1
XS GIS Cut Line= 6
2260132.35025326708023.7763068742260319.74632239708113.951560253
2260386.54973143708090.7981059822260492.82788219708058.914660756
2260572.15693043708038.4181602542260615.47094369707894.866906271
#Sta/Elev= 30
       0 1864.11    21.7 1855.76    42.9  1851.1    58.6  1846.5     133 1839.68
   164.1 1841.61   181.8 1838.98     204 1840.49   218.4 1838.93   233.7  1838.7
   248.8 1841.05   271.8 1841.69   305.3 1840.28   310.6  1838.9   321.9 1830.67
     326 1829.61   334.3 1829.77   338.4 1827.56  342.35 1824.06   346.8 1822.41
   355.3  1822.3   365.11824.059   372.1  1828.4   376.3 1829.84   396.4 1833.72
   463.4 1833.32   514.7 1844.62   535.6 1847.27   573.2 1850.18   621.6 1858.37
#Mann= 5 ,-1,0
       0      .1       0      60     .08       0     170      .1       0
  342.35    .045       0   365.1      .1       0
Bank Sta=342.35,365.1
XS Rating Curve= 0 ,0
Exp/Cntr(USF)=0,0
Exp/Cntr=0.3,0.1

Type RM Length L Ch R = 1 ,202     ,64.7,62.1,61.8
XS GIS Cut Line= 6
2260144.42399161708061.6406490692260331.82006074708151.815902449
2260398.62346979708128.6624481782260504.90162054708096.779002952
2260584.23066878 708076.282502452260627.54468204707932.731248466
#Sta/Elev= 30
       0 1851.84    26.4 1843.92    50.4  1840.3    98.4 1838.82   110.7 1837.11
   132.9 1840.21   146.5 1838.76   158.3  1835.2   174.1 1833.96   186.2 1834.19
   212.5 1837.39   254.6 1835.61     267 1836.65   317.6  1836.1   344.5 1830.77
  355.971823.517   360.3  1822.3  367.741823.519   388.9 1827.81   398.6 1827.88
   413.8 1830.07   463.4 1830.74   474.9 1832.09   483.2 1834.48   500.3 1834.76
   508.3 1836.42   516.6 1840.35   562.6 1845.78   587.7 1847.31   621.6  1853.4
#Mann= 5 ,-1,0
       0      .1       0      50     .08       0     160      .1       0
  355.97    .045       0  367.74      .1       0
Bank Sta=355.97,367.74
XS Rating Curve= 0 ,0
Exp/Cntr(USF)=0,0
Exp/Cntr=0.3,0.1

Type RM Length L Ch R = 1 ,140     ,,,
XS GIS Cut Line= 4
2260170.64962127708096.8228132692260412.45138326708235.977067414
2260642.25307332708057.9548434882260674.03403799 707943.91466126
#Sta/Elev= 30
       0 1839.96     105 1834.32   139.1 1836.59   206.4 1834.26     224  1832.3
   259.2 1832.17   298.9 1828.69   312.1 1825.74   329.3 1825.96   349.2 1823.24
   374.9 1823.87  404.731819.574   415.2 1818.68   427.2 1819.58   450.7 1825.25
   470.9 1824.69     481 1828.34   496.2 1826.96   506.3 1824.24   518.7 1825.52
   538.3  1831.2   545.9  1831.1   570.5 1835.07   591.3 1835.67   595.4 1836.31
   607.9 1841.71   641.1 1845.53   657.7 1845.97   674.3  1851.1   688.1 1852.34
#Mann= 6 ,-1,0
       0     .08       0     140      .1       0  404.73    .045       0
   427.2      .1       0  498.98    .025       0  528.98      .1       0
Bank Sta=404.73,427.2
XS Rating Curve= 0 ,0
Exp/Cntr(USF)=0,0
Exp/Cntr=0.3,0.1
LCMann Table=0

Chan Stop Cuts=-1
Use User Specified Reach Order=0
Composite Channel Slope=5